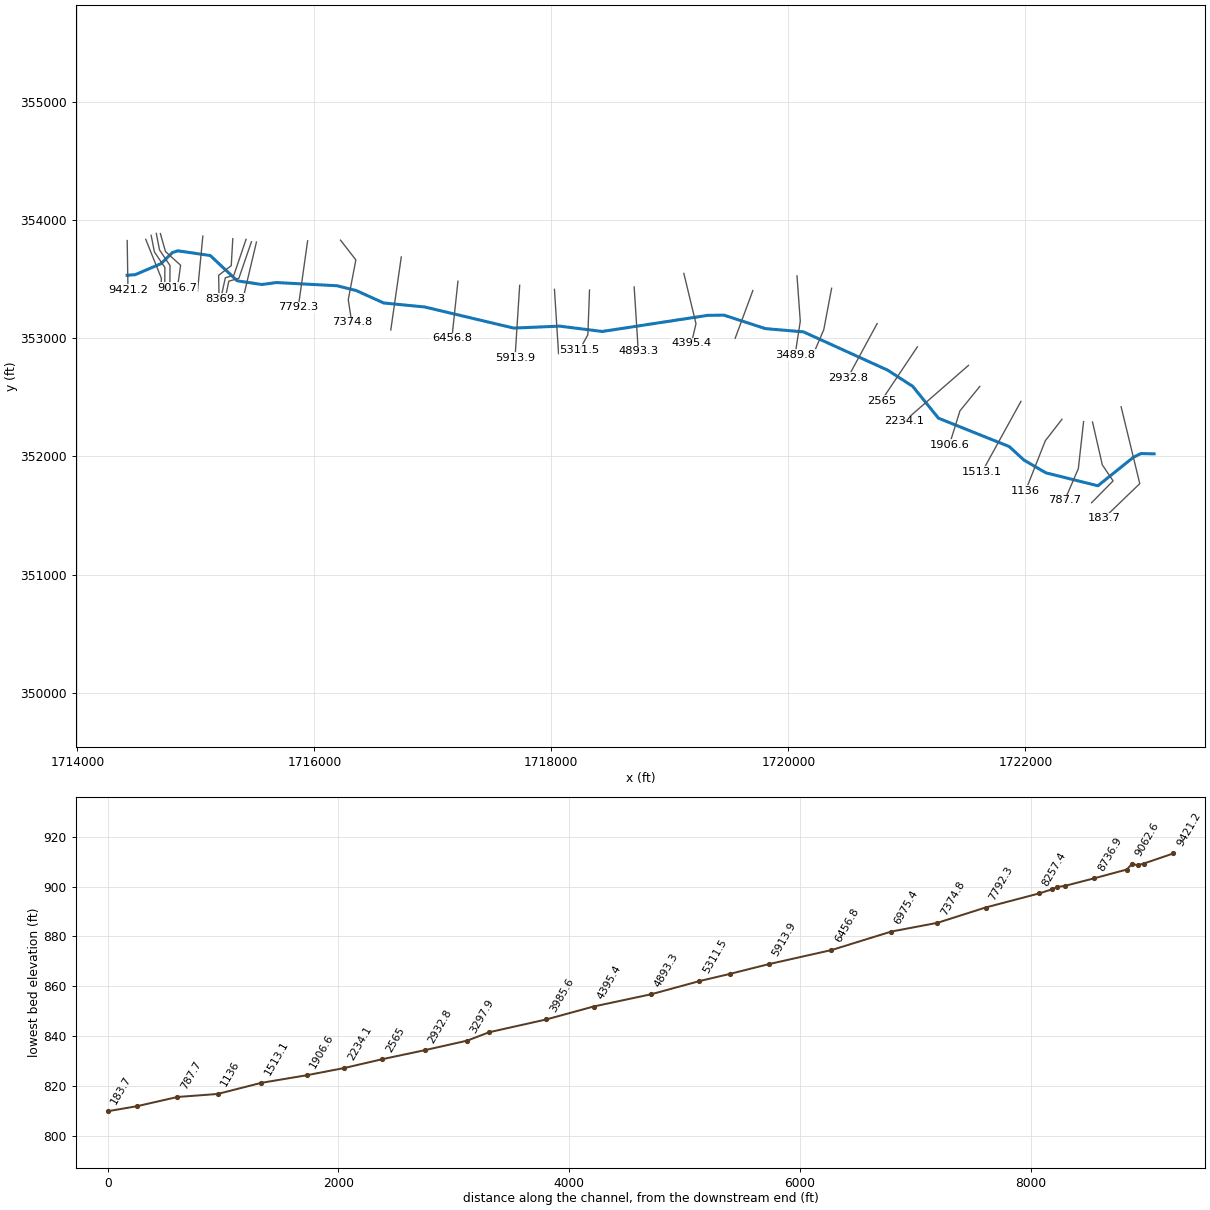
--- MEADOWFK.prj (project) ---

Proj Title=MEADOWFK
Current Plan=p01
Default Exp/Contr=0,0
English Units
Geom File=g01
Flow File=f01
Plan File=p01
BEGIN DESCRIPTION:
END DESCRIPTION:
DSS Export Rating Curves= 0
DSS Export Rating Curve Sorted= 0
DSS Export Volume Flow Curves= 0
DXF OffsetX= 0
DXF OffsetY= 0
DXF ScaleX= 0
DXF ScaleY= 0

--- MEADOWFK.p01 (plan) ---

Plan Title=Floodplain
Program Version=4.00
Geom File=g01
Flow File=f01
K Sum by GR=0
Std Step Tol=0.01
Critical Tol=0.01
Num of Std Step Trials=20
Max Error Tol=0.3
Flow Tol Ratio=0.001
Split Flow NTrial=30
Split Flow Tol=0.02
Split Flow Ratio=0.02
Log Output Level=0
Friction Slope Method=1
Unsteady Friction Slope Method=2
Unsteady Bridges Friction Slope Method=1
Global Log Level=0
CheckData=False
Run HTab=0
Run UNet=0
Run PostProcess=0
UNET Theta=0
UNET Theta Warmup=0
UNET ZTol=0
UNET ZSATol=0
UNET MxIter=0
UNET MaxInSteps=0
UNET DtIC=0
UNET DtMin=0
UNET MaxCRTS=0
UNET WFStab=0
UNET SFStab=0
UNET WFX=0
UNET SFX=0
UNET DSS MLevel=0
UNET DZMax Abort=0
UNET Convert EG Bridges=0
UNET Use Existing IB Tables=0
UNET Froude Limit=0
UNET Froude Power=0
Write IC File=0
Echo Input=False
Echo Output=False
Write Detailed=0

--- MEADOWFK.f01 (steady flow) ---

Flow Title=NFF Regression Equation
Program Version=4.00
Number of Profiles=1
Profile Names=P100yr
River Rch & RM=MEADOWFK,Main      ,9421.2
899.5407
River Rch & RM=MEADOWFK,Main      ,5913.9
1004.704
River Rch & RM=MEADOWFK,Main      ,3489.8
1063.016
River Rch & RM=MEADOWFK,Main      ,3297.9
1290.083
River Rch & RM=MEADOWFK,Main      ,440.2
1338.975
Boundary for River Rch & Prof#=MEADOWFK,Main      ,1
Up Type=0
Dn Type=3
Dn Slope=0.007344

--- MEADOWFK.g01 (geometry) ---

Geom Title=USGS 10m DEM
Program Version=4.10

River Reach=MEADOWFK        ,Main
Reach XY= 30
     1714420.448      353532.205     1714488.226      353537.205
     1714706.559      353630.539     1714803.434      353724.965
     1714849.441      353738.855     1715122.011      353698.924
     1715349.441      353485.382     1715556.039      353454.132
     1715681.038      353470.625     1716191.455      353443.715
     1716353.781      353402.917     1716585.552      353297.882
     1716931.906      353264.028     1717682.774      353085.642
     1718069.059      353102.135     1718429.302      353056.997
     1719319.059      353193.282      1719457.08      353195.017
     1719806.038      353081.302     1720128.087      353053.525
     1720839.024      352729.566     1721049.962      352592.847
     1721266.976       352323.75     1721864.198       352083.82
     1721987.462      351970.105     1722173.226      351861.598
     1722612.462      351752.222     1722910.205      351991.806
     1722975.309      352024.792      1723086.42      352021.962

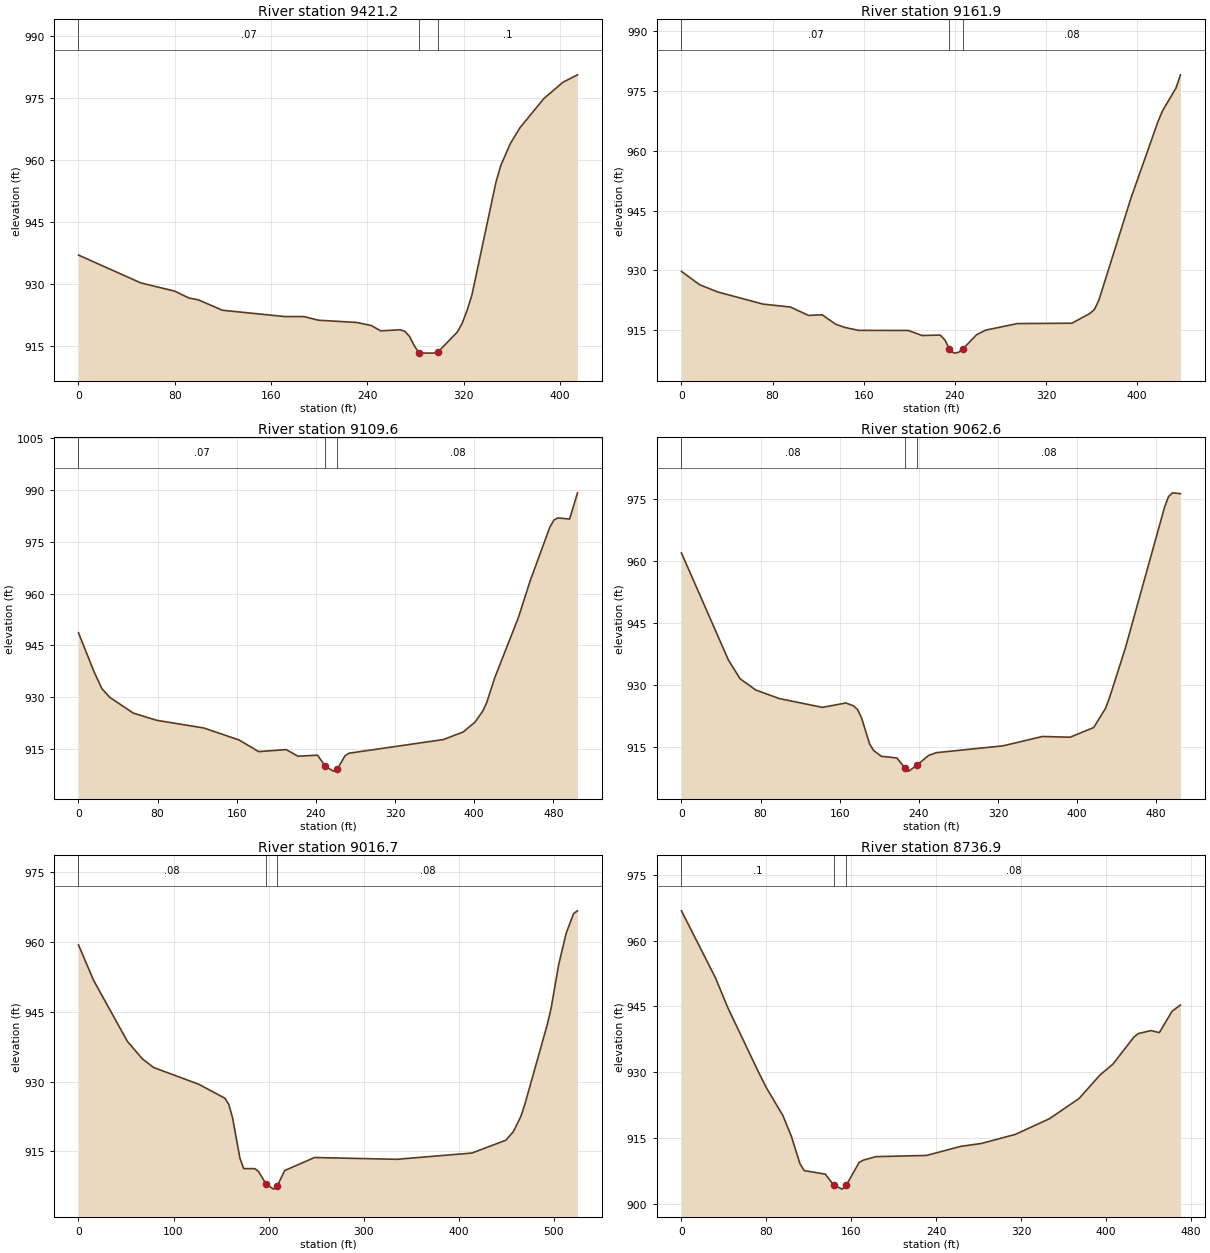
Type RM Length L Ch R = 1 ,9421.2  ,250.6,259.3,267.6
XS GIS Cut Line= 2
     1714420.938      353825.891     1714427.448      353411.394
#Sta/Elev= 30
       0  937.02    51.8  930.29    79.7  928.33    91.7  926.65    99.6  926.21
   119.6  923.69   171.4  922.17   187.3  922.16   199.3  921.29   231.2  920.74
   243.2  920.01   251.1  918.72   267.1  918.98     271  918.64     275   917.4
     279  915.12     283  913.37     295  913.34     299   913.7   314.9  918.48
   318.9  920.63   322.9   923.7   326.8  927.28   346.8  954.55   350.8  958.58
   358.7   963.9   366.7  967.73   386.6   974.8   402.6  978.76   414.6  980.54
#Mann= 3 , 0 , 0
       0     .07       0     283    .045       0     299      .1       0
Bank Sta=283,299
XS Rating Curve= 0 ,0
Exp/Cntr=0.3,0.1

Type RM Length L Ch R = 1 ,9161.9  ,47.3,52.2,57
XS GIS Cut Line= 3
     1714577.318      353836.307     1714709.262      353507.141
      1714705.79      353423.807
#Sta/Elev= 30
       0  929.76    15.9  926.42    31.9  924.59    71.7  921.54    95.6  920.82
   111.6   918.7   123.5  918.86   135.5  916.47   143.4  915.69   155.4  914.96
   199.2  914.93   211.2  913.66   227.1  913.78   231.1   912.6   235.1  910.36
   239.1  909.24   243.1  909.42     247  910.28     259  913.85     267  915.01
   294.9  916.66   342.7  916.75   358.6  919.21   362.6  920.25   366.5  922.61
   394.3  947.95   418.2  967.32   422.2  970.04   434.1  975.81     438  979.11
#Mann= 3 , 0 , 0
       0     .07       0   235.1    .045       0     247     .08       0
Bank Sta=235.1,247
XS Rating Curve= 0 ,0
Exp/Cntr=0.3,0.1

Type RM Length L Ch R = 1 ,9109.6  ,47.2,47.1,47
XS GIS Cut Line= 4
     1714623.151      353869.641     1714650.445      353729.856
     1714738.986      353597.911      1714737.25      353394.786
#Sta/Elev= 30
       0  948.69    15.8  937.34    23.7   932.5    31.6  929.99    55.4  925.42
    79.1  923.33   126.6  921.11   162.3  917.64   182.2  914.26     210  914.85
   221.9  912.93   241.7  913.23   249.7  909.98   257.6  908.61   261.6  909.13
   269.5  913.07   273.5   913.8     369  917.76     389  919.96   400.9  922.81
   408.9  926.08   412.8  928.53   420.8  935.62   444.7  953.07   456.7  963.77
   476.6   979.3   480.6  981.31   484.5  981.95   496.5  981.63   504.5  989.22
#Mann= 3 , 0 , 0
       0     .07       0   249.7    .045       0   261.6     .08       0
Bank Sta=249.7,261.6
XS Rating Curve= 0 ,0
Exp/Cntr=0.3,0.1

Type RM Length L Ch R = 1 ,9062.6  ,40.1,45.9,51.7
XS GIS Cut Line= 4
     1714666.554      353886.134     1714693.847      353746.349
     1714782.389      353614.405     1714780.653       353411.28
#Sta/Elev= 30
       0  961.89    47.5  935.98    59.3  931.46    75.2  928.74    98.9  926.68
   142.4  924.55   166.3  925.61   174.2  924.89   178.2  923.97   182.2  921.94
   190.1  915.78   194.1  914.17     202  912.72   217.9  912.31   225.8  909.92
   229.8  909.13   237.8  910.52   249.7   912.9   257.6  913.59   325.2  915.25
     365  917.51   392.9  917.33   416.8  919.68   428.8  924.35   432.8  926.92
   448.7   938.8   488.5  973.02   492.5  975.55   496.5  976.43   504.5  976.22
#Mann= 3 , 0 , 0
       0     .08       0   225.8    .045       0   237.8     .08       0
Bank Sta=225.8,237.8
XS Rating Curve= 0 ,0
Exp/Cntr=0.3,0.1

Type RM Length L Ch R = 1 ,9016.7  ,301.1,279.8,257.6
XS GIS Cut Line= 4
     1714700.929      353884.919     1714743.985      353732.835
     1714871.762      353616.863     1714844.679      353424.502
#Sta/Elev= 30
       0  959.39    15.8   951.8    51.4  938.65    67.2  934.88      79  933.02
   126.4  929.43   154.1   926.4   158.1  925.08     162  922.27   169.8  913.53
   173.8  911.28   185.5  911.27   189.4  910.66   197.3  907.97   205.1  906.87
     209   907.5   216.9  910.87   248.3  913.67   334.6  913.28   413.9  914.63
   449.6  917.39   457.5  919.25   465.4  922.54   469.4  925.01   493.2  942.32
   497.1  945.73   505.1  955.12     513  961.91   520.9  966.14   524.9  966.71
#Mann= 3 , 0 , 0
       0     .08       0   197.3    .045       0     209     .08       0
Bank Sta=197.3,209
XS Rating Curve= 0 ,0
Exp/Cntr=0.3,0.1

Type RM Length L Ch R = 1 ,8736.9  ,277.5,258.6,239.4
XS GIS Cut Line= 2
     1715059.262      353863.391     1715014.124      353395.335
#Sta/Elev= 30
       0   966.8    31.9   951.6    43.8  944.67    71.7  930.51    79.7  926.62
    95.6  920.13   103.6   915.4   111.6  909.21   115.6   907.6   135.5   906.8
   143.5  904.29   151.4  903.38   155.4  904.32   167.4  909.45   171.4  909.99
   183.3  910.78   231.1  911.06     263  913.12   282.9   913.8   314.8  915.87
   346.7  919.42   374.6  924.02   394.5  929.42   406.5  931.85   426.4  938.06
   430.4  938.82   442.3  939.51   450.3  939.05   462.3  943.92   470.2  945.34
#Mann= 3 , 0 , 0
       0      .1       0   143.5    .045       0   155.4     .08       0
Bank Sta=143.5,155.4
XS Rating Curve= 0 ,0
Exp/Cntr=0.3,0.1

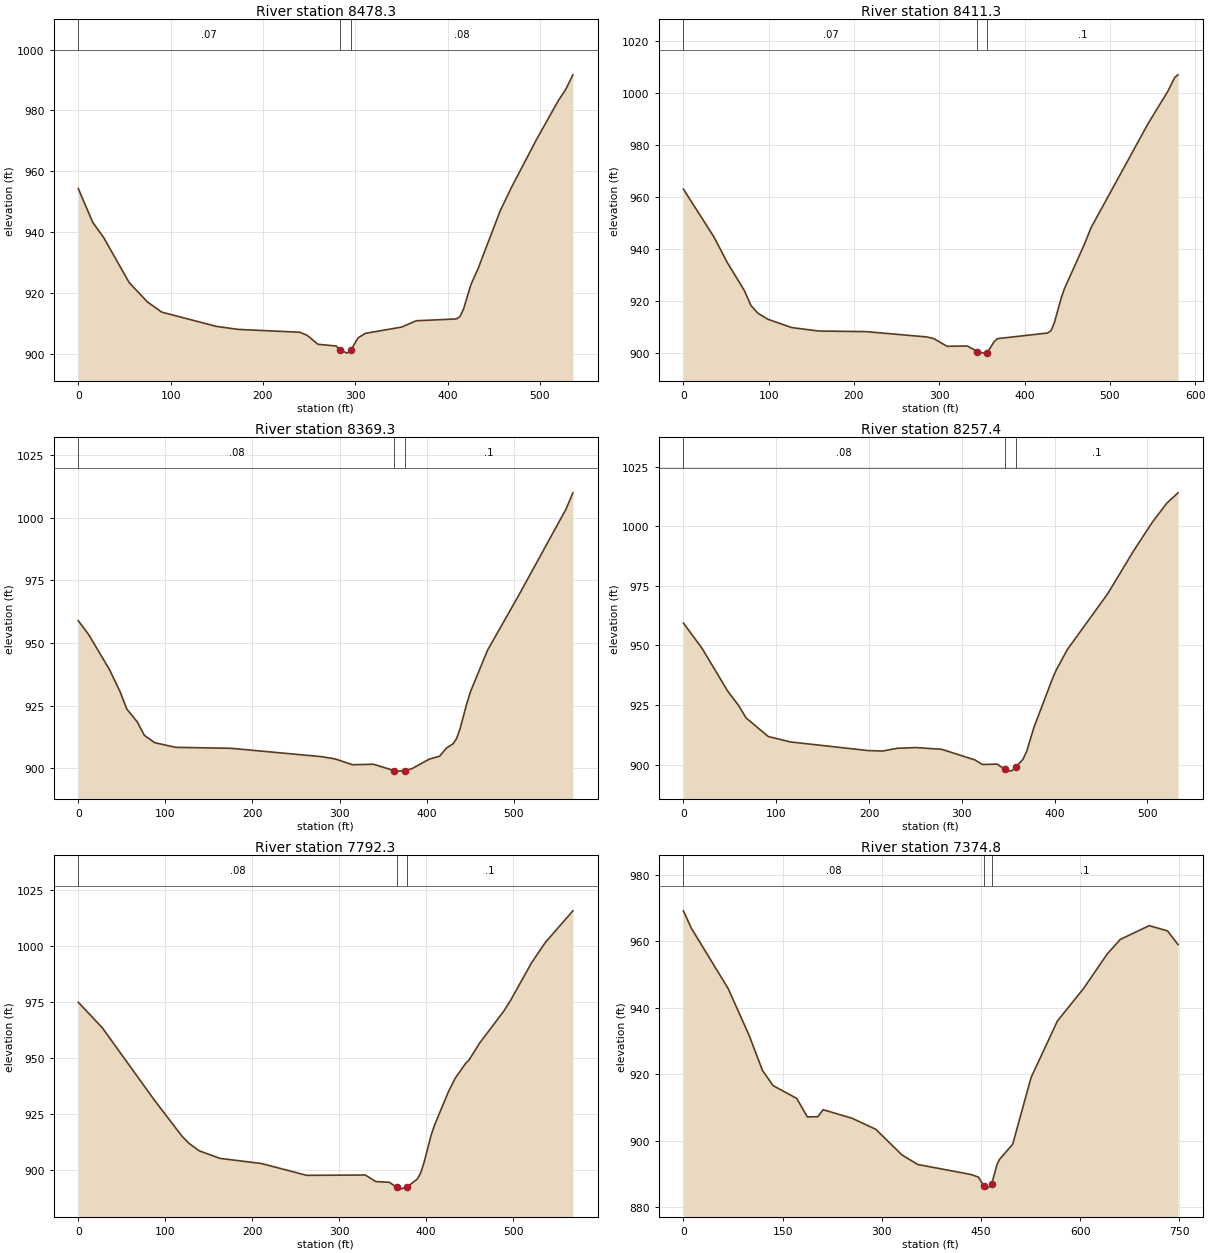
Type RM Length L Ch R = 1 ,8478.3  ,76.7,66.9,57.8
XS GIS Cut Line= 4
      1715311.99      353841.358     1715298.969      353613.493
     1715192.632      353532.113     1715195.887      353358.502
#Sta/Elev= 30
       0  954.34    15.7  943.24    27.6  938.21    55.1  923.47    74.8  917.12
    90.5  913.74   149.5  909.07   173.1  908.08     240  907.14   247.9  906.14
   259.7  903.19   279.4  902.61   283.4  901.39   291.2  900.28   295.2   901.2
   303.1  905.29   310.9  906.77   350.3  908.84   366.1  910.91   409.5  911.51
   413.4  912.24   417.4  914.81   425.3  922.76   433.2  928.13   456.8  946.84
   468.7   954.4   496.3   970.4     520  983.22   527.9  986.82   535.8   991.7
#Mann= 3 , 0 , 0
       0     .07       0   283.4    .045       0   295.2     .08       0
Bank Sta=283.4,295.2
XS Rating Curve= 0 ,0
Exp/Cntr=0.3,0.1

Type RM Length L Ch R = 1 ,8411.3  ,53.9,42,41.3
XS GIS Cut Line= 4
     1715424.019      353836.177      1715320.67      353532.113
     1715249.056      353511.497     1715209.993      353331.375
#Sta/Elev= 30
       0  962.96    35.7  944.61    51.5  934.68    71.4  923.97    79.3  918.15
    87.2  915.26    99.1  912.88   126.9   909.7   158.6  908.36   214.1  908.14
   285.5  906.08   293.4  905.48   309.2  902.48   332.9  902.61   344.7  900.48
   352.5  899.86   356.4   900.1   364.3  904.24   368.2  905.43     427   907.6
     431  908.45   434.9  911.46   442.7  920.72   446.6  924.51   470.2  941.74
     478  948.12   544.7  988.05   568.2 1000.68   576.1 1005.92     580 1006.92
#Mann= 3 , 0 , 0
       0     .07       0   344.7    .045       0   356.4      .1       0
Bank Sta=344.7,356.4
XS Rating Curve= 0 ,0
Exp/Cntr=0.3,0.1

Type RM Length L Ch R = 1 ,8369.3  ,74.2,111.9,137.8
XS GIS Cut Line= 4
     1715469.325      353815.316     1715362.988      353506.071
     1715278.353        353482.2     1715246.886       353332.46
#Sta/Elev= 30
       0  958.91      12  953.34    35.9  939.38    47.9   930.7    55.8  923.66
    67.8  918.53    75.8  913.24    87.7  910.28   111.7  908.42   175.5  908.03
   279.2   904.7   295.1  903.78     315  901.48     339  901.68     363   899.1
     367  898.93     375  899.18     383  899.89     403   903.7     415  904.89
   422.8  908.13   430.6   909.9   434.6  912.03   438.5  915.94   446.3  926.05
   450.3  930.52   469.9  947.08   505.2  968.66   560.1 1003.39     568 1009.89
#Mann= 3 , 0 , 0
       0     .08       0     363    .045       0     375      .1       0
Bank Sta=363,375
XS Rating Curve= 0 ,0
Exp/Cntr=0.3,0.1

Type RM Length L Ch R = 1 ,8257.4  ,462.6,465.1,466.8
XS GIS Cut Line= 2
     1715511.643      353813.146      1715389.03      353294.483
#Sta/Elev= 30
       0  959.38    19.9  948.89    47.7  930.86    59.7  924.68    67.6  919.56
    91.5  911.79   115.3  909.52   198.9   905.9   214.8  905.72   230.7  906.87
   250.6  907.16   278.4  906.43   314.2  901.97   322.2  900.05   338.1  900.23
     346  898.08     350  897.28     354  897.45     358898.8748   365.9  902.24
   369.9  905.58   377.8  915.71   397.7  936.05   401.7  939.65   413.6   948.2
   457.4  971.79   485.2   989.7   505.1 1001.56     521  1009.7     533 1013.99
#Mann= 3 , 0 , 0
       0     .08       0     346    .045       0     358      .1       0
Bank Sta=346,358
XS Rating Curve= 0 ,0
Exp/Cntr=0.3,0.1

Type RM Length L Ch R = 1 ,7792.3  ,418.3,417.4,416.1
XS GIS Cut Line= 2
     1715943.464       353823.46     1715864.297      353260.266
#Sta/Elev= 30
       0   975.1    27.8  963.61    87.5  931.38   119.3  915.24   127.3  912.07
   139.2   908.7   163.1  905.34   210.8  903.05   262.5  897.78   330.1  897.92
     342  895.01   357.9  894.66   365.9  892.42   369.9  891.62   377.8  892.49
   389.8  896.14   393.7  898.84   397.7  903.69   405.7  915.75   409.6  920.16
   425.6  935.16   433.5  941.24   445.4  947.81   449.4  949.38   461.4  956.81
   489.2  971.11   497.1  975.95     521   992.6   536.9 1001.74   568.7 1015.92
#Mann= 3 , 0 , 0
       0     .08       0   365.9    .045       0   377.8      .1       0
Bank Sta=365.9,377.8
XS Rating Curve= 0 ,0
Exp/Cntr=0.3,0.1

Type RM Length L Ch R = 1 ,7374.8  ,398.2,399.5,400.3
XS GIS Cut Line= 4
     1716221.026      353829.239     1716350.478       353662.25
     1716286.459      353325.879     1716315.756      353133.821
#Sta/Elev= 30
       0  969.14      12  963.91    67.8  945.72    99.7  931.54   119.6  921.15
   135.5  916.61   171.4  912.73   187.4  907.19   203.3  907.24   211.3  909.35
   255.1  906.77   290.9  903.46   330.7  895.72   354.6  892.87   434.2   889.9
   446.2   889.1   454.2  886.41   458.1  885.47   466.1  886.89   474.1  892.81
     478   894.4     498  898.99   525.8  919.04   565.6  936.02   605.2  945.81
   640.9  956.17   660.8  960.56   704.4  964.68   732.1  963.11     748     959
#Mann= 3 , 0 , 0
       0     .08       0   454.2    .045       0   466.1      .1       0
Bank Sta=454.2,466.1
XS Rating Curve= 0 ,0
Exp/Cntr=0.3,0.1

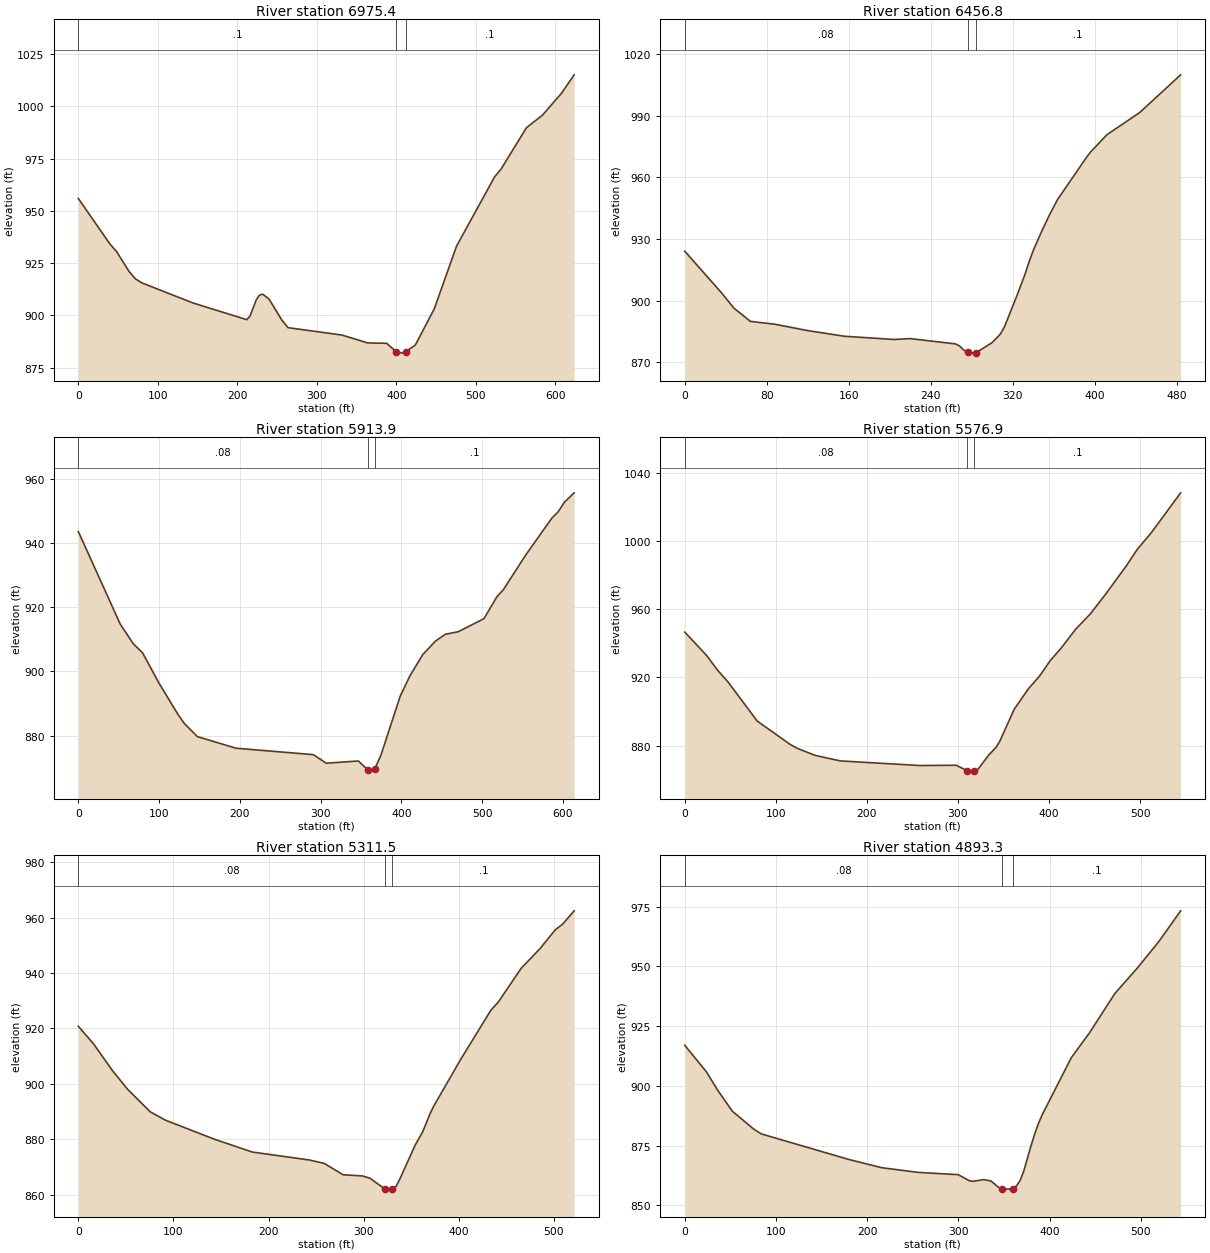
Type RM Length L Ch R = 1 ,6975.4  ,517.7,518.5,519.3
XS GIS Cut Line= 2
     1716733.785      353686.872     1716645.243      353069.684
#Sta/Elev= 30
       0  955.91      40  934.01      48   930.6      64  920.91    71.9  917.47
    79.9  915.55   143.9  905.99   211.8  897.97   215.8   899.6   223.8  907.51
   227.8   909.7   231.8  910.16   239.8  907.85   255.8  897.84   263.8  894.14
   331.7   890.6   363.7  886.86   387.7  886.66   399.7  882.64   407.7  881.97
   411.7  882.68   423.7   885.8   447.6  903.14   475.6  933.11   523.6  966.34
   531.6  969.95   563.6   989.8   583.5  995.68   607.5 1006.18   623.5 1015.03
#Mann= 3 , 0 , 0
       0      .1       0   399.7    .045       0   411.7      .1       0
Bank Sta=399.7,411.7
XS Rating Curve= 0 ,0
Exp/Cntr=0.3,0.1

Type RM Length L Ch R = 1 ,6456.8  ,541.8,542.9,543.7
XS GIS Cut Line= 2
     1717212.084      353482.011     1717160.868      353001.108
#Sta/Elev= 30
       0  924.06      36  903.74      48  896.38      64  889.97    87.9  888.58
   119.9  885.48   155.9  882.73   203.8  881.18   219.8  881.59   263.8  879.05
   267.8   878.1   271.8  876.19   275.8  874.98   279.8  874.54   283.8  874.64
   299.8  879.67   307.8  883.79   311.8  887.34   323.8  902.27   331.7  912.68
   335.7  918.79   339.7   924.2   347.7  933.34   355.7  941.72   363.7  949.28
   391.7  969.61   395.7  972.23   411.7  980.68   443.6  991.43   483.6 1009.79
#Mann= 3 , 0 , 0
       0     .08       0   275.8    .045       0   283.8      .1       0
Bank Sta=275.8,283.8
XS Rating Curve= 0 ,0
Exp/Cntr=0.3,0.1

Type RM Length L Ch R = 1 ,5913.9  ,333.9,337,339.7
XS GIS Cut Line= 2
     1717732.917      353447.288     1717693.854      352834.441
#Sta/Elev= 30
       0  943.62    51.8   914.8    67.8  908.72    79.8  905.71    99.7  896.43
   123.6  886.51   131.6  883.67   147.5  879.66   195.4  876.04   291.1  874.04
     307  871.37   346.9  872.06   358.9  869.19   362.9   868.9   366.9  869.43
   374.8   873.9   398.8  892.36   410.7  898.62   426.7  905.27   442.6  909.52
   454.6  911.58   470.5  912.37   502.4  916.45   518.4  923.27   526.4  925.48
   554.3  936.36   586.2  947.71   594.2  949.75   602.1  952.79   614.1  955.69
#Mann= 3 , 0 , 0
       0     .08       0   358.9    .045       0   366.9      .1       0
Bank Sta=358.9,366.9
XS Rating Curve= 0 ,0
Exp/Cntr=0.3,0.1

Type RM Length L Ch R = 1 ,5576.9  ,267.6,265.4,263
XS GIS Cut Line= 2
      1718026.32      353413.434     1718061.042      352870.031
#Sta/Elev= 30
       0  946.63    23.8  933.03    35.8  924.43    47.7  917.21    79.5  894.42
   115.3  880.81   123.2  878.44   143.1  874.24   170.9  870.97   258.3  868.27
   298.1  868.42     310  865.27     314  864.98     318  865.24   321.9     866
   333.9  874.51   341.8  878.93   345.8  882.42   361.7  901.28   377.6  913.54
   389.5  920.76   401.4  929.97   413.4  937.32   429.2  948.34   445.2  957.27
     461  968.12   484.9  985.58   496.8   995.2   512.7 1005.32   544.5 1028.48
#Mann= 3 , 0 , 0
       0     .08       0     310    .045       0     318      .1       0
Bank Sta=310,318
XS Rating Curve= 0 ,0
Exp/Cntr=0.3,0.1

Type RM Length L Ch R = 1 ,5311.5  ,415.8,418.2,420.4
XS GIS Cut Line= 3
     1718322.327      353407.358     1718308.438      353029.754
     1718239.861      352903.886
#Sta/Elev= 30
       0   920.8    15.9   914.5    35.8  904.86    51.7   898.1    75.6  889.95
    91.5  886.95   143.2  880.05     183  875.44   242.6   872.6   258.5  871.35
   278.4  867.25   298.3  866.85   306.3  866.06   322.2  862.14   326.2  862.08
   330.1  862.17   334.1  863.12   338.1  865.81     354   877.9     362  882.74
   369.9  889.42   373.9  892.19   401.8  908.77   433.6  926.54   441.6  929.59
   465.4  941.64   485.4  948.82   501.3  955.54   509.2  957.65   521.2  962.41
#Mann= 3 , 0 , 0
       0     .08       0   322.2    .045       0   330.1      .1       0
Bank Sta=322.2,330.1
XS Rating Curve= 0 ,0
Exp/Cntr=0.3,0.1

Type RM Length L Ch R = 1 ,4893.3  ,493.7,497.9,501.6
XS GIS Cut Line= 2
     1718699.063      353433.399     1718733.785      352890.865
#Sta/Elev= 30
       0  916.96      24  905.72      36  898.23      52  889.44      76  881.78
      84  879.89   179.9   869.2   215.9  865.76   255.8   863.8   299.8  862.86
   311.8  860.33   315.8  860.07   327.8  860.77   335.8  860.19   343.8   857.6
   347.8   856.8   359.8  856.86   363.8  858.25   367.8  860.52   371.8  864.56
   379.8  875.22   383.8  880.07   387.8  884.33   391.7  887.79   423.7  911.75
   443.7   922.2   471.7  938.74   495.7  949.08   519.7  960.36   543.6  973.23
#Mann= 3 , 0 , 0
       0     .08       0   347.8    .045       0   359.8      .1       0
Bank Sta=347.8,359.8
XS Rating Curve= 0 ,0
Exp/Cntr=0.3,0.1

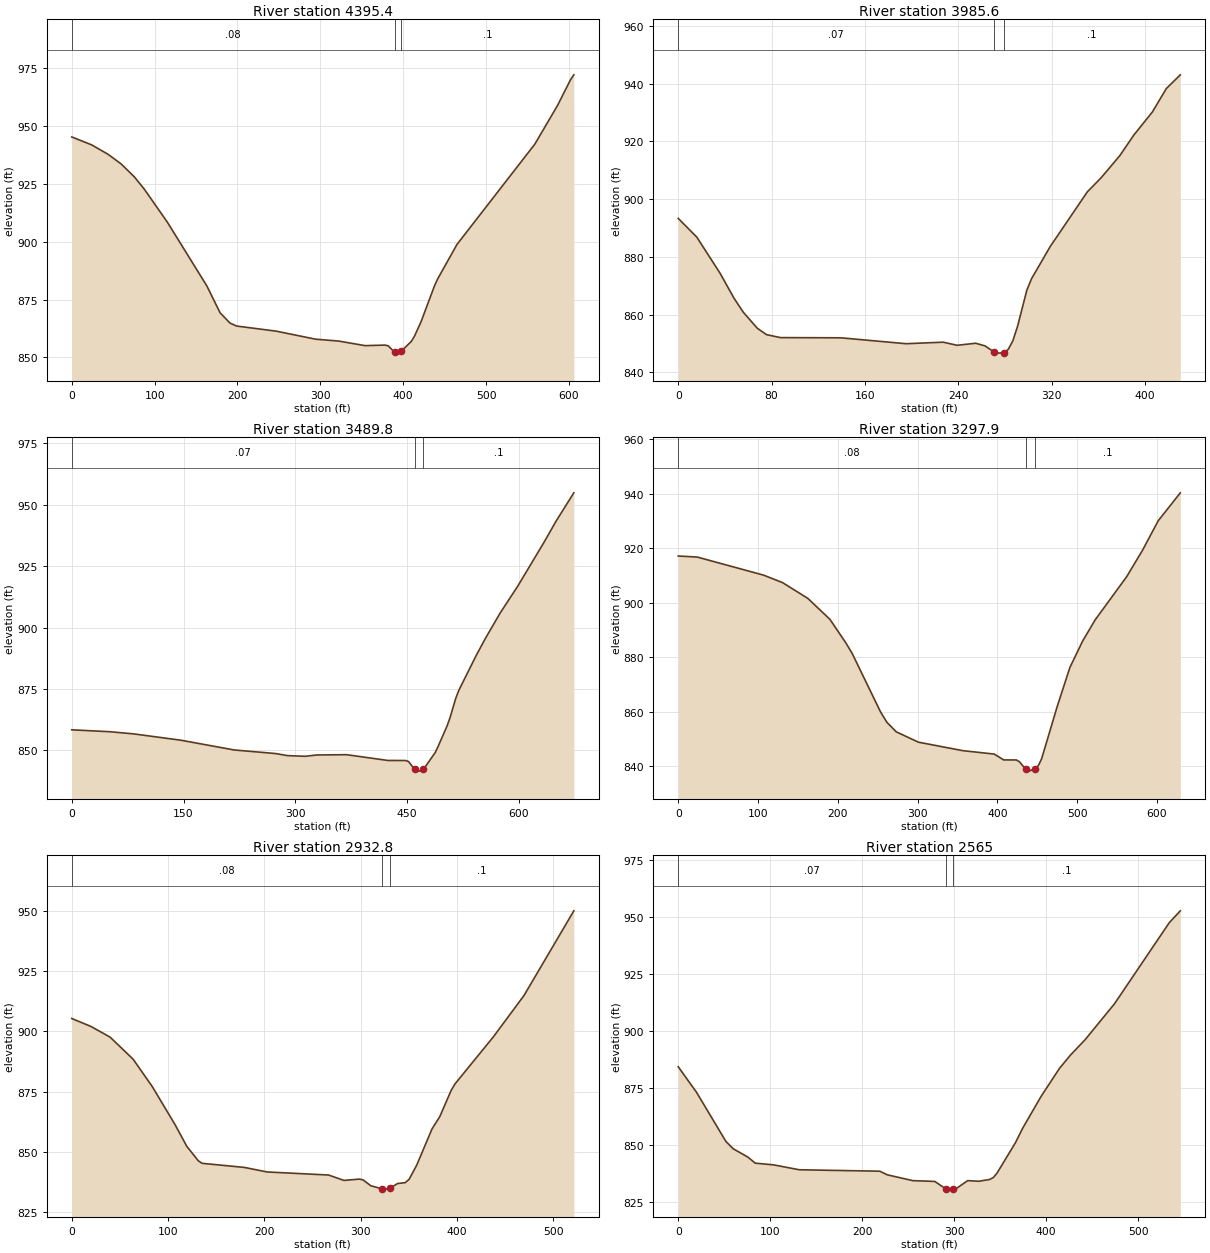
Type RM Length L Ch R = 1 ,4395.4  ,423.1,409.8,395.6
XS GIS Cut Line= 3
     1719118.334      353547.983     1719220.764      353122.636
      1719182.57      352958.573
#Sta/Elev= 30
       0  945.37    23.9  941.96    43.8  937.87    59.7  933.66    75.6  928.08
    87.5  922.82   115.3  908.56   163.1  880.92     179  869.35   190.9  864.91
   198.9   863.6   246.6   861.4   294.3  857.92   322.2   857.1     354  855.13
   377.8  855.36   381.8  855.09   389.8  852.22   393.8  851.89   397.7  852.75
   409.7   856.9   413.6  859.18   421.6  865.47   437.5   880.7   441.4  883.84
   464.9  898.86     559   942.3   586.4  959.04     602  970.11     606  972.23
#Mann= 3 , 0 , 0
       0     .08       0   389.8    .045       0   397.7      .1       0
Bank Sta=389.8,397.7
XS Rating Curve= 0 ,0
Exp/Cntr=0.3,0.1

Type RM Length L Ch R = 1 ,3985.6  ,490.9,495.8,500.1
XS GIS Cut Line= 2
     1719700.799      353403.018     1719551.493      352999.372
#Sta/Elev= 30
       0  893.34    15.9  886.87    35.9  874.33    47.8  865.72    55.8  860.85
    67.7  855.34    75.7  853.09    87.7  852.07   139.5     852   195.3  849.96
   227.1  850.49   239.1  849.41     255  850.12     263   849.2     271  847.04
     275   846.7     279  846.86   282.9     848   286.9  851.01   290.9     856
   298.9  868.59   302.9  872.47   318.8  883.55   350.7  902.52   362.6  907.43
   378.6  915.09   390.5  922.15   406.5  930.19   418.4  938.27   430.4  943.03
#Mann= 3 , 0 , 0
       0     .07       0     271    .045       0     279      .1       0
Bank Sta=271,279
XS Rating Curve= 0 ,0
Exp/Cntr=0.3,0.1

Type RM Length L Ch R = 1 ,3489.8  ,197.5,191.9,185.9
XS GIS Cut Line= 3
     1720073.195      353527.149     1720100.972      353143.469
     1720056.702      352857.879
#Sta/Elev= 30
       0  858.38    51.6   857.6    83.3  856.72   146.7  854.13   218.1  850.17
   273.6  848.72   289.5  847.87   313.3   847.6   329.2  848.14   368.8  848.25
   424.3   845.9     448  845.88     452  845.44   459.9   842.3   463.9  841.56
   467.8  841.64   471.8  842.24   487.6  849.08   491.6  851.63   503.4  859.82
   507.4  863.17   515.3  871.26   519.3  874.42     543  888.84   554.9  895.54
   574.7  905.87   598.5  916.92   634.1  934.96   649.9  943.37   673.7  954.89
#Mann= 3 , 0 , 0
       0     .07       0   459.9    .045       0   471.8      .1       0
Bank Sta=459.9,471.8
XS Rating Curve= 0 ,0
Exp/Cntr=0.3,0.1

Type RM Length L Ch R = 1 ,3297.9  ,367.2,365.1,363
XS GIS Cut Line= 3
      1720365.34      353422.338     1720299.151       353071.86
     1720191.729      352821.209
#Sta/Elev= 30
       0  917.07    23.8  916.69     107  910.06   130.8  907.31   162.5  901.53
   190.2  893.83     210  885.26     218  881.37   253.6  859.89   261.6  856.08
   273.4  852.57   301.2  848.78   356.7  845.68   396.2  844.42     408  842.28
   423.9  842.26   427.8   841.6   435.7  838.79   439.7  838.17   447.6  839.12
   451.5  840.24   455.5  842.66   475.2  861.98     491   876.2   506.9  885.85
   522.7  893.67   562.2   909.5     582  919.17   601.7     930   629.4  940.25
#Mann= 3 , 0 , 0
       0     .08       0   435.7    .045       0   447.6      .1       0
Bank Sta=435.7,447.6
XS Rating Curve= 0 ,0
Exp/Cntr=0.3,0.1

Type RM Length L Ch R = 1 ,2932.8  ,369.8,367.8,365.5
XS GIS Cut Line= 2
      1720749.41      353123.504     1720501.146       352665.17
#Sta/Elev= 30
       0  905.38    19.9  902.09    39.8  897.63    63.7  888.45    83.6  877.03
   107.4  861.09   119.4   852.2   131.3  846.19   135.3  845.11   179.1  843.41
   202.9  841.51   266.6  840.24   282.5     838   298.4  838.54   302.4  838.22
   310.4  835.78   322.3  834.46   326.3  834.37   330.3  834.71   338.2   836.7
   346.2  837.07   350.2  838.46   358.1  844.36     374  859.46     382  864.51
   393.9  875.53   397.9   878.2   437.7  897.78   469.5  914.98   521.2  950.21
#Mann= 3 , 0 , 0
       0     .08       0   322.3    .045       0   330.3      .1       0
Bank Sta=322.3,330.3
XS Rating Curve= 0 ,0
Exp/Cntr=0.3,0.1

Type RM Length L Ch R = 1 ,2565    ,337.1,331,324.9
XS GIS Cut Line= 2
      1721088.82      352926.455     1720785.868      352472.462
#Sta/Elev= 30
       0  884.32    19.9  873.13    51.8  851.65    59.8  848.42    75.7  844.78
    83.7  842.13   103.6  841.38   131.5  839.24   219.1   838.6   227.1  837.04
     255  834.47   278.9  834.13   290.8  830.89   294.8  830.76   298.8  830.82
   302.8  831.18   314.7  834.48   326.7   834.2   338.6  834.99   342.6  835.86
   346.6   837.8   366.5  851.03   374.5  857.46   394.4  871.31   414.3  883.52
   426.3  889.39   442.2  896.11   474.1   911.8   533.8  947.37   545.8  952.56
#Mann= 3 , 0 , 0
       0     .07       0   290.8    .045       0   298.8      .1       0
Bank Sta=290.8,298.8
XS Rating Curve= 0 ,0
Exp/Cntr=0.3,0.1

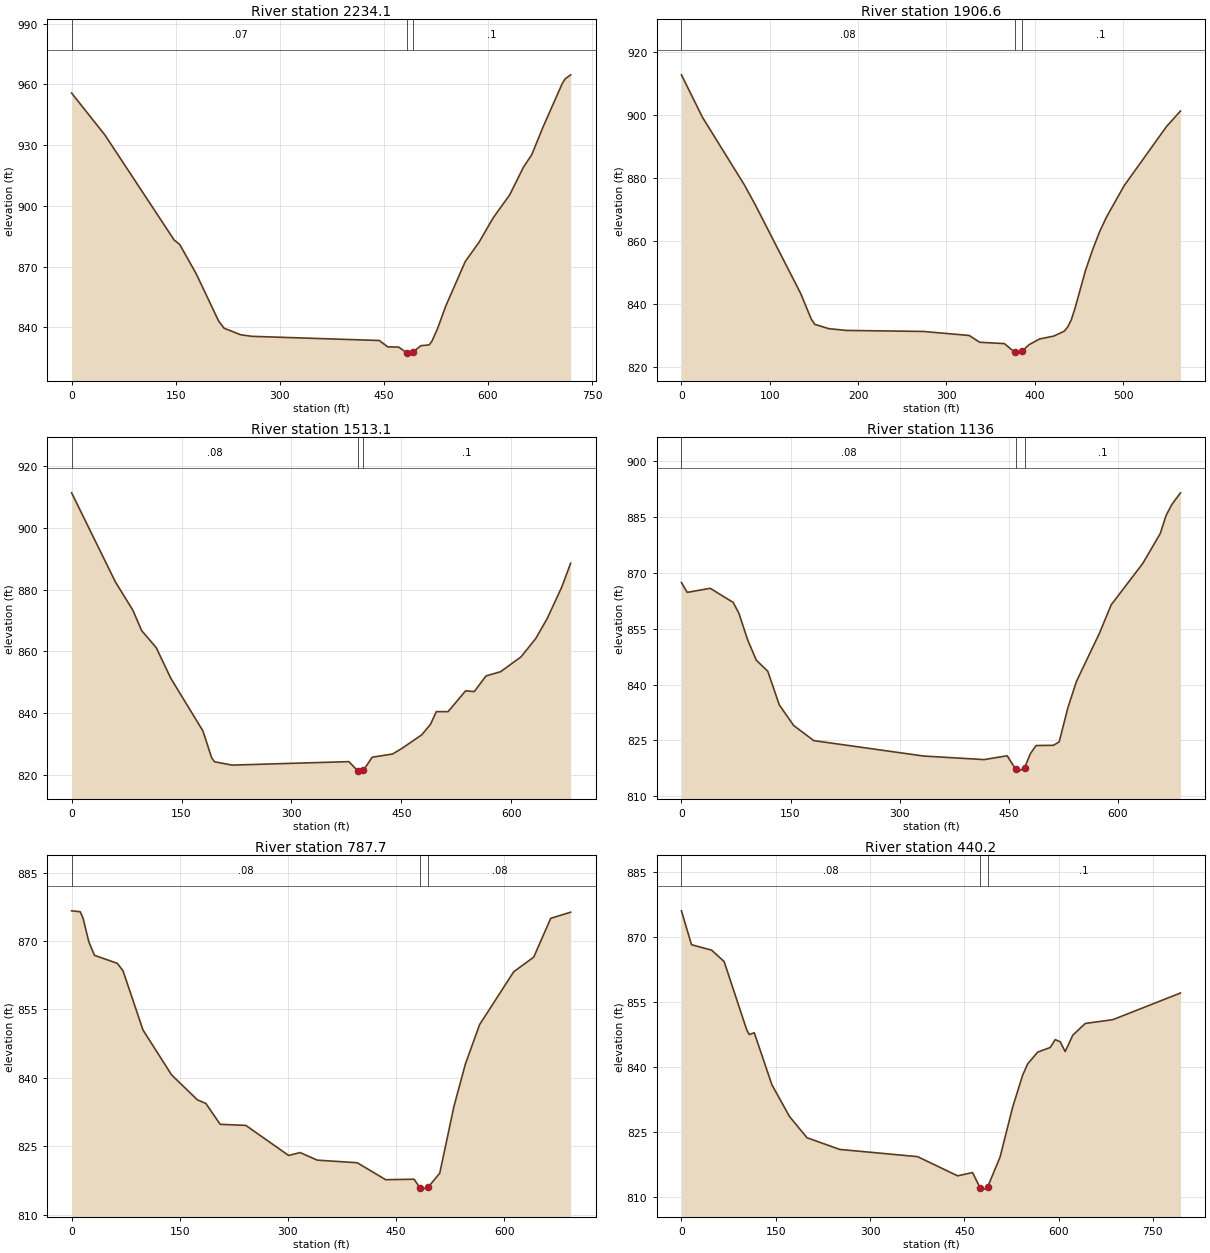
Type RM Length L Ch R = 1 ,2234.1  ,314.5,327.5,339.9
XS GIS Cut Line= 2
     1721520.243      352770.205     1720978.577      352297.115
#Sta/Elev= 30
       0  955.72      48     935   147.8  883.09   155.8  880.91   179.8  866.26
   211.8  843.13   219.8   839.5   243.7  836.28   259.7   835.5   443.5  833.44
   455.5  830.32   471.5  830.16   483.4   827.3   487.4   827.2   491.4  827.56
   503.4  830.86   515.4  831.27   519.4  833.17   527.4  839.33   539.4  850.62
   567.4  872.51   587.3  882.05   607.3  893.93   631.3  905.38   651.3  919.13
   663.2  925.26   679.2  938.76   707.2  960.48   711.2   962.7   719.2  964.73
#Mann= 3 , 0 , 0
       0     .07       0   483.4    .045       0   491.4      .1       0
Bank Sta=483.4,491.4
XS Rating Curve= 0 ,0
Exp/Cntr=0.3,0.1

Type RM Length L Ch R = 1 ,1906.6  ,398.1,393.5,388.5
XS GIS Cut Line= 3
     1721615.729      352592.254     1721448.195      352385.656
     1721359.653      352100.066
#Sta/Elev= 30
       0  912.74    23.8  899.24    71.5  877.64    83.4  871.52     135  843.25
   146.9  835.15   150.9  833.44   166.7  832.06   186.6   831.5     274  831.17
   325.8  829.89   337.8  827.73   365.7  827.31   377.6  824.49   381.6  824.28
   385.6  824.86   393.6  826.97   405.5  828.78   421.5  829.69   433.4  831.26
   437.4  832.61   441.4  834.89   445.4  838.35   457.4  850.48   465.3  856.98
   473.3  862.78   481.3  867.56   501.2  877.48     549  896.23     565  901.25
#Mann= 3 , 0 , 0
       0     .08       0   377.6    .045       0   385.6      .1       0
Bank Sta=377.6,385.6
XS Rating Curve= 0 ,0
Exp/Cntr=0.3,0.1

Type RM Length L Ch R = 1 ,1513.1  ,374,377,380.1
XS GIS Cut Line= 2
     1721962.945      352465.967     1721634.827      351869.163
#Sta/Elev= 30
       0  911.32    59.7  882.51    83.6  873.32    95.6  866.72   115.5   861.2
   135.4  851.28   179.2  834.25   191.2  825.51   195.2  824.25     219  823.18
   378.4   824.3   390.3  821.42   394.3  821.23   398.3   821.5   410.2  825.73
   438.1  826.78     450  828.46   477.9  832.98   489.9  836.41   497.8  840.49
   513.8  840.48   537.7  847.22   549.6  846.98   565.6  852.05   585.5  853.41
   613.4  858.22   633.3  864.09   649.2  870.66   669.1  880.87   681.1  888.52
#Mann= 3 , 0 , 0
       0     .08       0   390.3    .045       0   398.3      .1       0
Bank Sta=390.3,398.3
XS Rating Curve= 0 ,0
Exp/Cntr=0.3,0.1

Type RM Length L Ch R = 1 ,1136    ,348.8,348.3,347.4
XS GIS Cut Line= 3
     1722309.306      352314.476     1722168.681      352133.052
     1722001.139      351708.155
#Sta/Elev= 30
       0  867.32     7.9   864.7    39.6  865.78    71.2     862    79.2  859.01
      91     852   102.9  846.52   118.7  843.56   134.6  834.52   154.4     829
     182  824.96   332.8  820.83   416.2  819.87     448  820.89   459.9  817.22
   463.9  816.78   471.8  817.63   479.8  821.43   487.7  823.64   511.5   823.7
   519.5  824.62   531.4  833.73   543.3  840.85   575.1  853.83     591  861.35
   634.6  872.49   658.5  880.47   666.4  885.26   674.4  888.24   686.3  891.38
#Mann= 3 , 0 , 0
       0     .08       0   459.9    .045       0   471.8      .1       0
Bank Sta=459.9,471.8
XS Rating Curve= 0 ,0
Exp/Cntr=0.3,0.1

Type RM Length L Ch R = 1 ,787.7   ,324.3,347.5,371
XS GIS Cut Line= 3
     1722491.597      352294.511     1722447.327      351896.941
     1722331.875      351628.712
#Sta/Elev= 30
       0  876.62    11.9  876.42    15.8  875.04    23.8  869.87    31.7  866.86
    63.4   865.1    71.3  863.46      99  850.47   138.6  840.64   174.3  835.17
   186.2  834.36     206  829.79   241.6  829.55     301  822.95   316.8  823.59
   340.6  821.93   396.1  821.36   435.5  817.64     475  817.74   482.9815.8918
   486.8  815.57   494.7  816.04   510.5  819.07   530.2  833.72     546  842.98
   565.8  851.67   613.1  863.26   640.8  866.46   664.4  874.97     692  876.32
#Mann= 3 , 0 , 0
       0     .08       0   482.9    .045       0   494.7     .08       0
Bank Sta=482.9,494.7
XS Rating Curve= 0 ,0
Exp/Cntr=0.3,0.1

Type RM Length L Ch R = 1 ,440.2   ,263.9,256.5,247.8
XS GIS Cut Line= 4
      1722567.12      352291.536     1722649.585      351929.123
     1722740.731      351793.706     1722559.307      351608.811
#Sta/Elev= 30
       0  875.97      16  868.17      48  866.92    67.9   864.3   103.9  848.56
   107.9  847.48   115.9   847.9   143.9  835.93   171.8  828.65   199.8  823.73
   251.8  821.04   375.7  819.38   439.4  814.96   463.2  815.72   475.2  812.18
   483.2   811.9   487.1  812.35     507  819.31     527  830.77   542.9  838.13
   550.8  840.72   566.8  843.44   586.7   844.5   594.7  846.32   602.7  845.82
   610.6  843.56   622.6  847.33   642.5  850.04   686.4  850.91     794  857.05
#Mann= 3 , 0 , 0
       0     .08       0   475.2    .045       0   487.1      .1       0
Bank Sta=475.2,487.1
XS Rating Curve= 0 ,0
Exp/Cntr=0.3,0.1

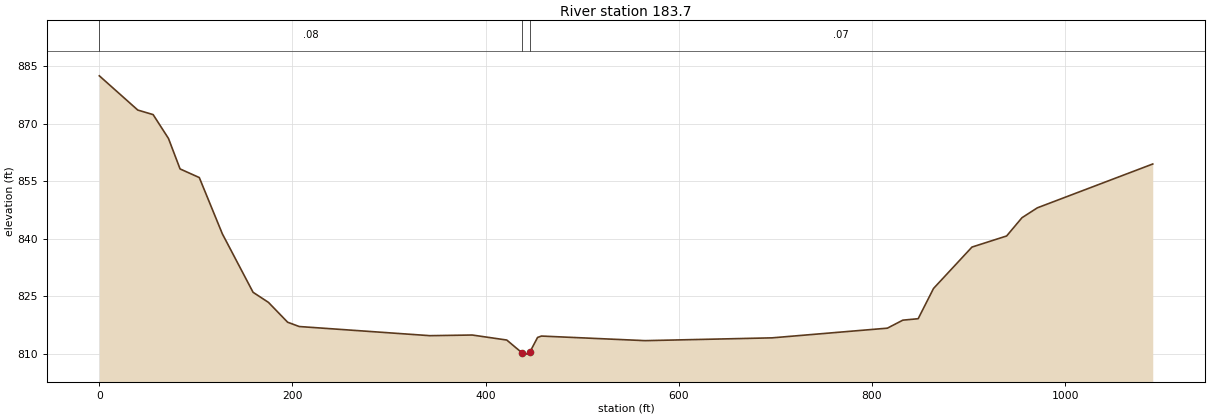
Type RM Length L Ch R = 1 ,183.7   ,193.5,183.7,173.8
XS GIS Cut Line= 3
     1722808.438      352420.162     1722965.773      351770.205
     1722661.953      351477.236
#Sta/Elev= 30
       0  882.54    39.8   873.6    55.7  872.41    71.6  866.18    83.6  858.22
   103.5  855.97   127.4  841.26   159.2     826   175.1  823.37     195  818.18
     207  817.06   342.3  814.67   386.1  814.84   421.9  813.53   437.9  810.14
   441.8  809.85   445.8  810.37   453.8  814.21   457.8  814.57   565.2  813.37
   696.6   814.1     816  816.63     832  818.72   847.9   819.1   863.8     827
   903.6  837.81   939.5  840.71   955.4  845.48   971.3  848.06  1090.8  859.51
#Mann= 3 , 0 , 0
       0     .08       0   437.9    .045       0   445.8     .07       0
Bank Sta=437.9,445.8
XS Rating Curve= 0 ,0
Exp/Cntr=0.3,0.1

Chan Stop Cuts=-1
Use User Specified Reach Order=0
Composite Channel Slope=5